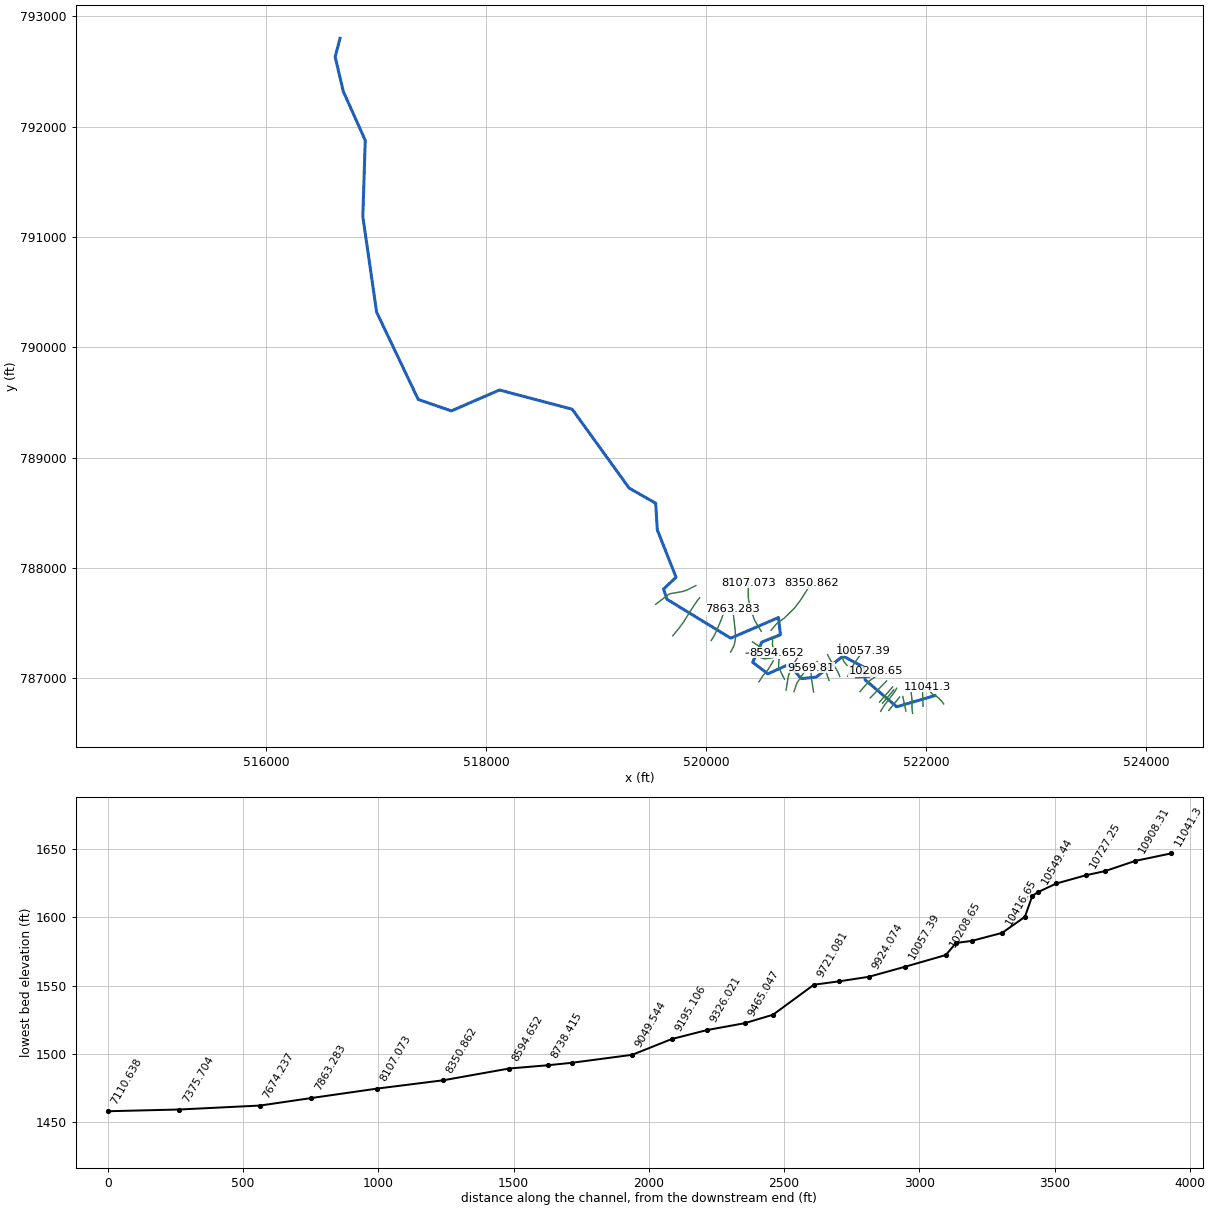
--- 5321_ras.prj (project) ---

Proj Title=5321
Current Plan=p01
Default Exp/Contr=0.3,0.1
English Units
Geom File=g01
Flow File=f01
Plan File=p01
Y Axis Title=Elevation
X Axis Title(PF)=Main Channel Distance
X Axis Title(XS)=Station
BEGIN DESCRIPTION:
RFD model 5321 exported to HEC-RAS
END DESCRIPTION:

--- 5321_ras.p01 (plan) ---

Plan Title=Plan 01
Program Version=4.10
Short Identifier=Plan 01
Geom File=g01
Flow File=f01
Subcritical Flow
Calc Critical at every XS
Secant Critical Depth

--- 5321_ras.f01 (steady flow) ---

Flow Title=Flow 01
Program Version=5.01
Number of Profiles= 6
Profile Names=10yr,25yr,50yr,100yr,100plus,500yr
River Rch & RM=5321,47, 11041.3
  471.78  765.24 1043.23 1299.86 1897.79 2885.38
River Rch & RM=5321,47,10908.31
  474.25  769.27 1048.76 1306.78  1907.9  2898.7
River Rch & RM=5321,47,10727.25
  478.85  776.81 1059.11 1319.73 1926.81 2923.61
River Rch & RM=5321,47,10617.14
  480.69  779.82 1063.24 1324.91 1934.36 2933.55
River Rch & RM=5321,47,10549.44
  482.23  782.33 1066.68 1329.21 1940.65 2941.83
River Rch & RM=5321,47,10416.65
  484.06  785.33  1070.8 1334.38 1948.19 2951.75
River Rch & RM=5321,47,10304.61
   486.5  789.32 1076.29 1341.25 1958.22 2964.95
River Rch & RM=5321,47,10208.65
  498.07  808.27  1102.3 1373.82 2005.77 3027.36
River Rch & RM=5321,47,10057.39
  499.87  811.24 1106.38 1378.93 2013.24 3037.16
River Rch & RM=5321,47,9924.074
  501.37   813.7 1109.77 1383.18 2019.44 3045.33
River Rch & RM=5321,47,  9813.6
  503.17  816.66 1113.84 1388.28 2026.89 3055.11
River Rch & RM=5321,47, 9569.81
  506.17  821.58 1120.61 1396.77 2039.29 3071.39
River Rch & RM=5321,47,9465.047
  507.66  824.04 1123.99 1401.01 2045.48 3079.52
River Rch & RM=5321,47,9326.021
  509.16  826.49 1127.37 1405.25 2051.67 3087.64
River Rch & RM=5321,47,9195.106
  509.76  827.47 1128.72 1406.95 2054.14 3090.88
River Rch & RM=5321,47,9049.544
  651.06  1058.7 1446.09  1804.1 2633.99 3832.89
River Rch & RM=5321,47,8825.137
  653.04 1061.96 1450.58 1809.74 2642.22 3843.32
River Rch & RM=5321,47,8738.415
  653.61 1062.89 1451.86 1811.35 2644.57  3846.3
River Rch & RM=5321,47,8350.862
  856.45 1395.81  1909.8 2385.31 3482.56 4882.47
River Rch & RM=5321,47,7863.283
  862.81 1406.31  1924.3 2403.53 3509.16 4914.96
River Rch & RM=5321,47,7674.237
 1009.89 1648.47 2258.15 2822.68 4121.11  5651.1
River Rch & RM=5321,47,7375.704
 1042.66 1702.64 2333.02  2916.9 4258.67 5815.28
River Rch & RM=5321,47,7110.638
 1047.94 1711.38 2345.12 2932.14 4280.92 5841.84
River Rch & RM=5321,47,6888.125
 1049.95 1714.71 2349.72 2937.94 4289.39 5851.94
River Rch & RM=5321,47,6644.336
 1053.97 1721.37 2358.94 2949.54 4306.33 5872.13
River Rch & RM=5321,47,6400.546
 1057.48 1727.18 2366.98 2959.67 4321.13 5889.77
River Rch & RM=5321,47,6156.757
 1062.24 1735.06 2377.89 2973.42 4341.19 5913.68
River Rch & RM=5321,47,5669.178
 1249.63 2044.45 2805.26 3510.77 5125.73 6832.02
River Rch & RM=5321,47,5181.599
 1313.36 2149.97 2951.31 3694.72 5394.29 7142.91
River Rch & RM=5321,47, 4694.02
 1319.32 2159.86 2965.02    3712 5419.51 7172.07
River Rch & RM=5321,47,4051.308
 1592.16 2612.21 3591.71 4501.79 6572.62 8484.44
River Rch & RM=5321,47,2743.704
 1604.66 2632.99 3620.56 4538.22  6625.8 8544.37
Boundary for River Rch & Prof#=5321,47,1
Up Type= 0
Dn Type= 2
Boundary for River Rch & Prof#=5321,47,2
Up Type= 0
Dn Type= 2
Boundary for River Rch & Prof#=5321,47,2
Up Type= 0
Dn Type= 2
Boundary for River Rch & Prof#=5321,47,2
Up Type= 0
Dn Type= 2
Boundary for River Rch & Prof#=5321,47,2
Up Type= 0
Dn Type= 2
Boundary for River Rch & Prof#=5321,47,2
Up Type= 0
Dn Type= 2

--- 5321_ras.g01 (geometry) ---

Geom Title=5321
Program Version=4.10

River Reach=5321,47
Reach XY= 30
522079.414534956786842.823633775521731.358979374786741.434744895
521444.692312688786985.323633775521431.914534956 787100.32363379
521243.581201583787200.879189342520999.692312717 787010.32363376
520864.692312688786996.434744895520749.692312688787124.768078208
520560.803423852787039.768078208520422.470090479787144.768078223
520505.803423822787328.101411551520674.692312717787394.212522671
520656.914534956 787550.32363379520223.303423822787363.031967118
519643.100698769  787716.0572844519613.060368299787808.344467118
519725.907590479787915.983355999519555.783681661788344.892915502
519541.002682418788586.773833752519299.785378814788723.563455641
 518782.26009509789438.739118829518121.161888212789612.876367763
517683.984944701789423.547272041517383.239272863789527.187021598
517004.595558107790319.711482316516879.702388614791185.832940117
516901.691105306791876.095565125516701.795218617792320.715056077
516628.327203721792632.297005638 516672.32254526792800.846717656

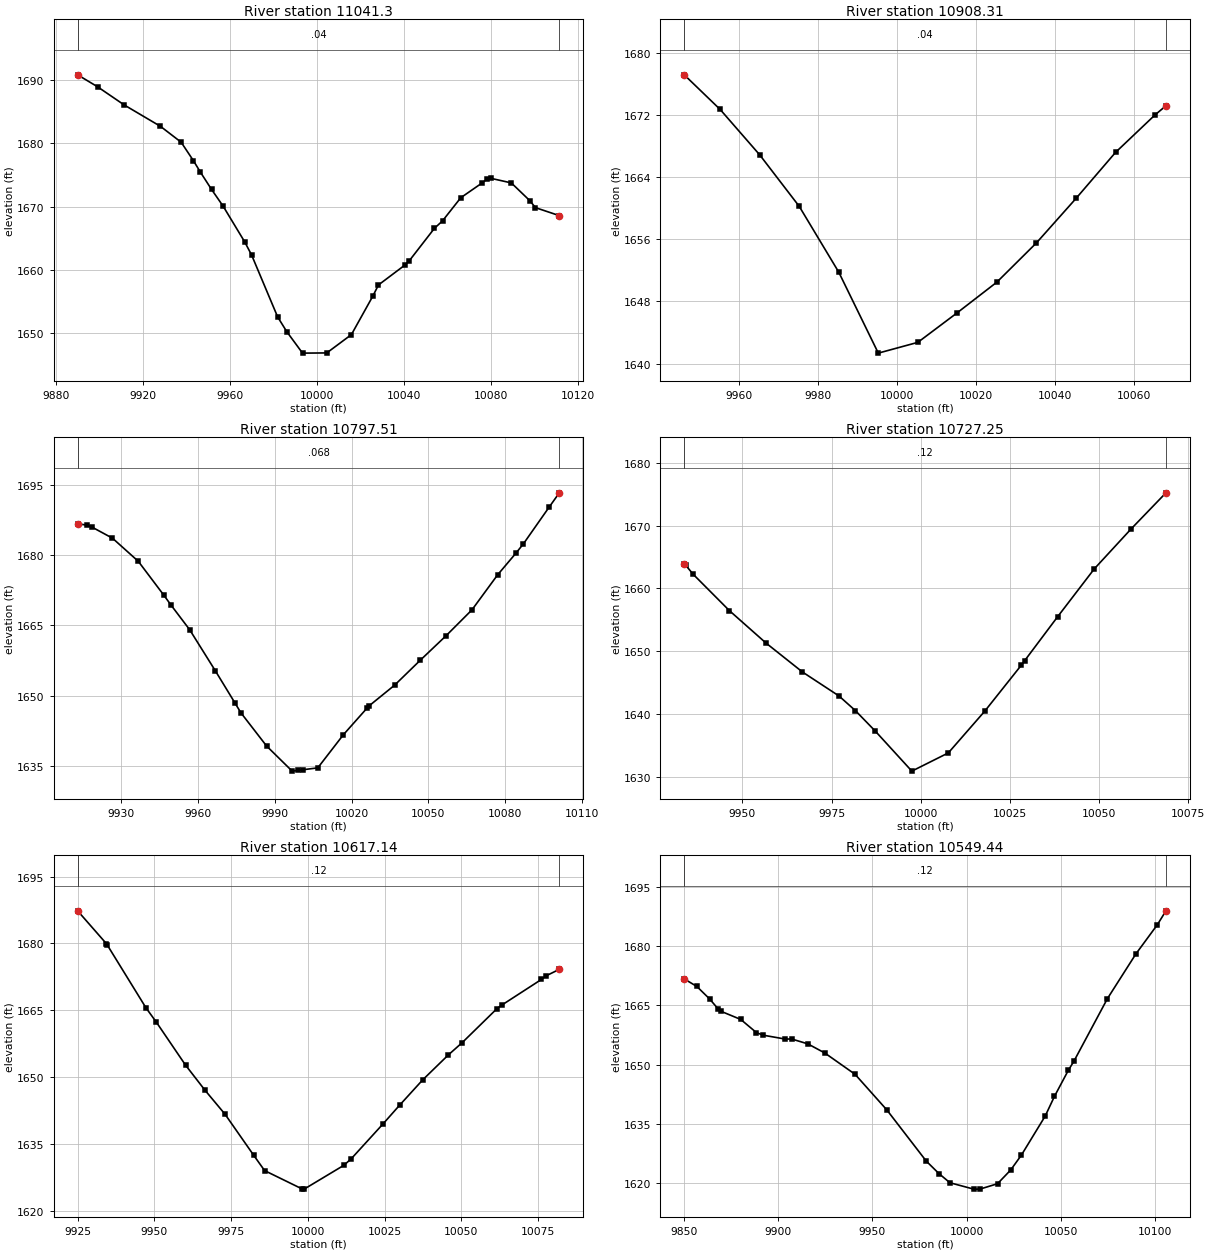
Type RM Length L Ch R = 1 , 11041.3,132.989700,132.989700,132.989700
XS GIS Cut Line= 6
522157.865307467786767.511891706522142.349898398786789.565289184
522106.094013572786826.226102158522052.422180027786858.432796478
522022.733939469786896.554418966522009.120518446786924.881760582
#Sta/Elev= 30
9890.017  1690.89899.1721688.9149911.3991686.0499928.0831682.6679937.5741680.164
9943.1891677.2629946.4331675.4329951.5511672.7059956.8431670.0799966.7831664.427
9969.958 1662.359981.9091652.5869986.0931650.2659993.3461646.87210004.491646.905
 10015.81649.79710025.631655.86610028.221657.63210040.351660.76510042.371661.444
10053.941666.57210057.651667.74610066.041671.40110075.781673.71810078.03 1674.33
10079.891674.46210089.26 1673.7410097.75 1670.9410100.361669.83410111.321668.575
#Mann= 3 , 0 , 0
9890.017    0.04       09890.017    0.04       010111.32    0.04       0
#XS Ineff= 2 , 0
       0                               0
Bank Sta=9890.017,10111.32
Exp/Cntr=0.3,0.1

Type RM Length L Ch R = 1 ,10908.31,110.799800,110.799800,110.799800
XS GIS Cut Line= 2
 521970.47838524786745.911826953521966.657611161786867.752066761
#Sta/Elev= 14
9946.1411677.1319955.233 1672.689965.2381666.8479975.2431660.2269985.2481651.769
9995.2531641.36510005.26 1642.7510015.261646.56510025.271650.49410035.271655.533
10045.281661.24310055.281667.15910065.291671.98610068.04 1673.15
#Mann= 3 , 0 , 0
9946.141    0.04       09946.141    0.04       010068.04    0.04       0
#XS Ineff= 2 , 0
       0                               0
Bank Sta=9946.141,10068.04
Exp/Cntr=0.3,0.1

Type RM Length L Ch R = 1 ,10797.51,70.262400,70.262400,70.262400
XS GIS Cut Line= 6
521875.680838018786681.473430888521871.259637713786717.642761663
521869.947427064786742.641070217521871.191551089786767.232991457
521871.624183923786794.378395915 521863.05734092786868.916933745
#Sta/Elev= 28
9912.9051686.6319916.4581686.3629918.517 1685.939926.5331683.5669936.6071678.648
9946.6811671.3649949.3441669.3659956.7111664.0599966.7251655.3269974.3771648.484
9976.7391646.3619986.7511639.3049996.7641633.946    99991634.104   100011634.243
10006.771634.64210016.771641.69910026.15 1647.4510026.771647.82510036.841652.277
10046.911657.61210056.971662.81910067.041668.308 10077.11675.78810084.16 1680.34
10087.171682.38810097.24 1690.2210101.181693.231
#Mann= 3 , 0 , 0
9912.905   0.068       09912.905   0.068       010101.18   0.068       0
#XS Ineff= 2 , 0
       0                               0
Bank Sta=9912.905,10101.18
Exp/Cntr=0.3,0.1

Type RM Length L Ch R = 1 ,10727.25,110.109900,110.109900,110.109900
XS GIS Cut Line= 2
521815.100239724786702.609720841521786.656699419 786834.63869147
#Sta/Elev= 18
9933.6871663.9699934.1631663.6559936.1331662.2929946.3621656.4639956.5911651.323
9966.8211646.709 9977.051642.8999981.6461640.574 9987.28 1637.289997.5091630.925
10007.741633.82710017.971640.481 10028.21647.78510029.13  1648.510038.431655.535
10048.661663.11610058.891669.41710068.751675.219
#Mann= 3 , 0 , 0
9933.687    0.12       09933.687    0.12       010068.75    0.12       0
#XS Ineff= 2 , 0
       0                               0
Bank Sta=9933.687,10068.75
Exp/Cntr=0.3,0.1

Type RM Length L Ch R = 1 ,10617.14,67.701800,67.701800,67.701800
XS GIS Cut Line= 2
521658.873033315786707.704086274521757.788628668786829.544326052
#Sta/Elev= 24
9924.9871687.3179934.3851679.9249934.7081679.5779947.2661665.5329950.574 1662.39
9960.1461652.687 9966.441647.0919973.0271641.6549982.3061632.4999985.9071629.017
9998.1711624.8879998.7881624.86110011.671630.18610014.041631.61110024.551639.549
 10029.91643.70910037.431649.39710045.771654.98410050.311657.76110061.631665.387
10063.19 1666.1710076.071671.911 10077.51672.69410081.921674.184
#Mann= 3 , 0 , 0
9924.987    0.12       09924.987    0.12       010081.92    0.12       0
#XS Ineff= 2 , 0
       0                               0
Bank Sta=9924.987,10081.92
Exp/Cntr=0.3,0.1

Type RM Length L Ch R = 1 ,10549.44,21.171100,21.171100,21.171100
XS GIS Cut Line= 6
521585.650550897786699.002636582521591.613542706786711.044355839
521620.704374254786756.646922678521699.187938452786858.940518796
521719.570508093786888.875511184521730.555623144 786908.99283272
#Sta/Elev= 30
 9850.131671.6899856.8221669.7819863.5671666.6429868.2591664.0299869.864 1663.46
9880.1211661.4459888.4581658.1119891.9821657.4719903.8431656.4779907.0521656.515
9915.7051655.2759924.7231652.9679940.7761647.5839957.6151638.5939978.5641625.643
9985.2671622.5029991.1071620.17910003.731618.56710006.981618.56510016.361619.929
10023.361623.40410028.991627.12810041.621636.98810046.591642.01310053.921648.579
10056.921650.90410074.691666.71710089.791678.00510101.181685.38310105.731688.893
#Mann= 3 , 0 , 0
 9850.13    0.12       0 9850.13    0.12       010105.73    0.12       0
#XS Ineff= 2 , 0
       0                               0
Bank Sta=9850.13,10105.73
Exp/Cntr=0.3,0.1

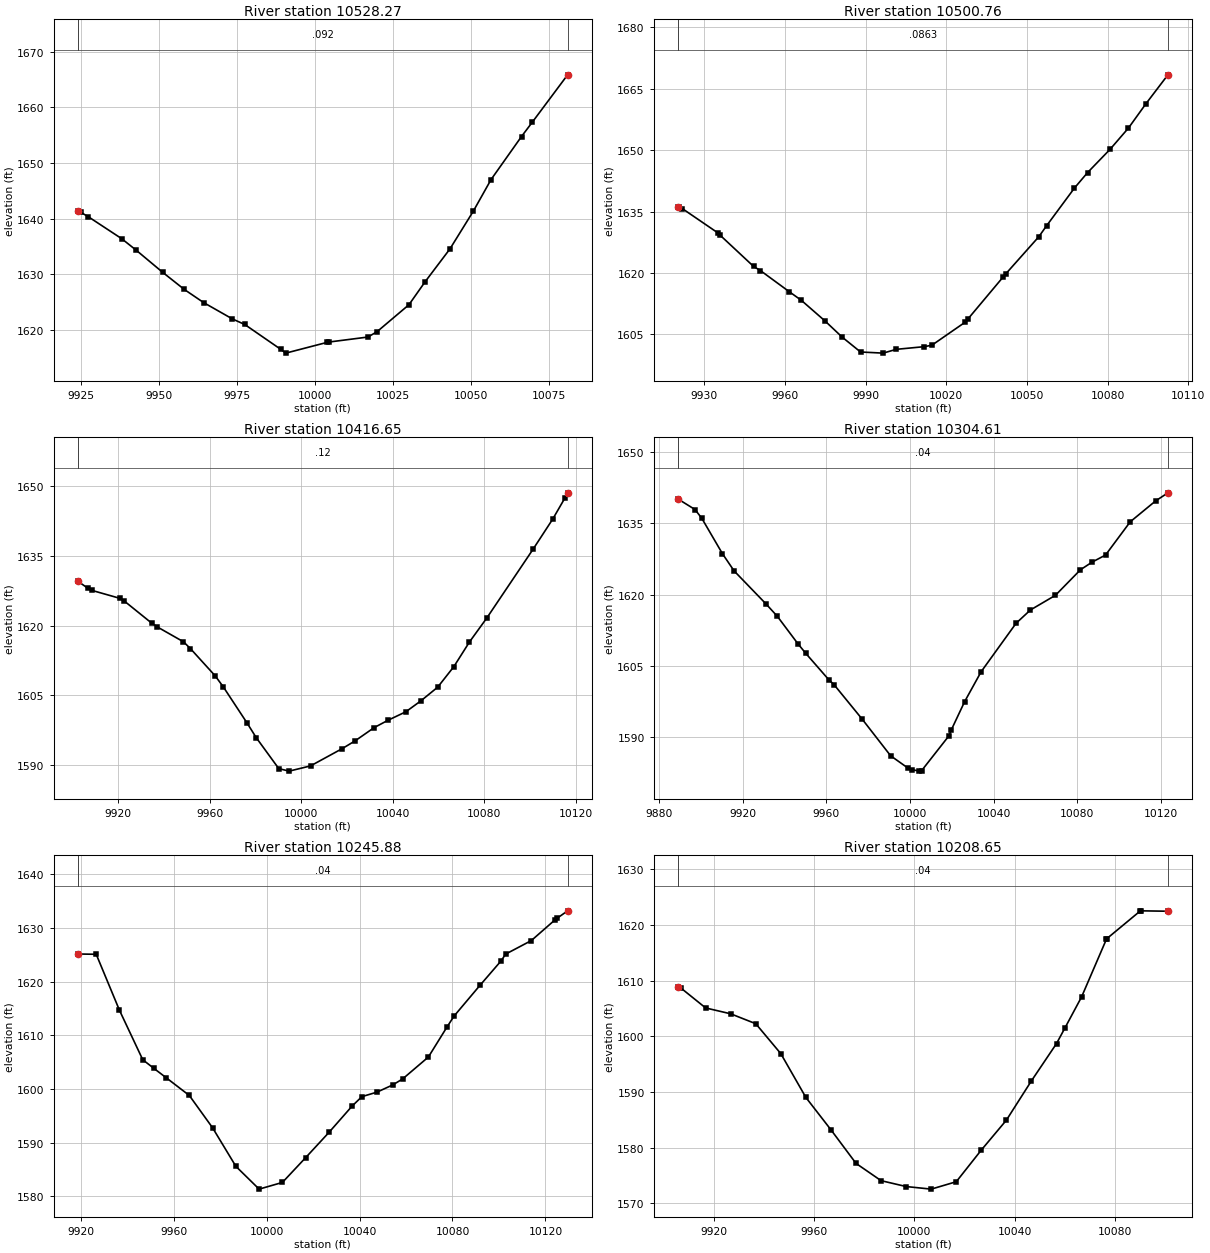
Type RM Length L Ch R = 1 ,10528.27,27.504500,27.504500,27.504500
XS GIS Cut Line= 2
521602.933407605786774.395565838521704.577511638786893.657981232
#Sta/Elev= 24
9924.1531641.3089924.9471641.1519927.3391640.3739938.0861636.4039942.7561634.322
9951.2261630.3489958.1721627.2589964.3651624.8969973.5891621.9519977.5041620.966
9989.0051616.5079990.6431615.81210003.781617.73210004.421617.80310016.921618.703
10019.841619.65810030.061624.51110035.261628.659 10043.2 1634.5610050.671641.337
10056.341647.01610066.091654.75710069.481657.28210080.851665.845
#Mann= 3 , 0 , 0
9924.153   0.092       09924.153   0.092       010080.85   0.092       0
#XS Ineff= 2 , 0
       0                               0
Bank Sta=9924.153,10080.85
Exp/Cntr=0.3,0.1

Type RM Length L Ch R = 1 ,10500.76,84.112100,84.112100,84.112100
XS GIS Cut Line= 2
521574.924810082786783.882348895521694.638977051 786921.21482721
#Sta/Elev= 28
9920.267 1636.059920.3811636.0329921.749 1635.749935.0151629.795  9935.61629.376
9948.2811621.6119950.8181620.6029961.5471615.4469966.0361613.3439974.8141608.319
9981.2551604.341 9988.081600.7199996.4731600.44110001.351601.36510011.691602.014
10014.611602.36910026.911607.95410027.88 1608.6610041.141619.04110042.131619.813
10054.411628.87110057.351631.59610067.68 1640.7710072.571644.54910080.941650.229
10087.781655.42610094.211661.29610102.451668.409
#Mann= 3 , 0 , 0
9920.267  0.0863       09920.267  0.0863       010102.45  0.0863       0
#XS Ineff= 2 , 0
       0                               0
Bank Sta=9920.267,10102.45
Exp/Cntr=0.3,0.1

Type RM Length L Ch R = 1 ,10416.65,112.036500,112.036500,112.036500
XS GIS Cut Line= 2
521490.899017423786821.829481065521639.525285095786975.876767576
#Sta/Elev= 30
9902.4591629.4869906.8651627.9699908.3651627.567 9920.761625.8399922.7681625.225
9934.6561620.518 9937.171619.6859948.5511616.5099951.5721615.0589962.447 1609.18
9965.9751606.8239976.3421599.0829980.3771595.9139990.2381589.262 9994.781588.726
10004.13 1589.8510018.031593.57810023.581595.21910031.92 1598.0710037.991599.649
10045.821601.48110052.391603.82910059.721606.76410066.791611.18110073.611616.473
10081.191621.617 10101.41636.379   101101642.853 10115.31647.35810116.521648.499
#Mann= 3 , 0 , 0
9902.459    0.12       09902.459    0.12       010116.52    0.12       0
#XS Ineff= 2 , 0
       0                               0
Bank Sta=9902.459,10116.52
Exp/Cntr=0.3,0.1

Type RM Length L Ch R = 1 ,10304.61,58.731200,58.731200,58.731200
XS GIS Cut Line= 6
521397.734988896786878.917495868521427.764704555786914.291703835
521471.759022027786962.561605886  521489.6144315786980.267609164
521508.686115652 786994.60676834521569.909823984787034.893377364
#Sta/Elev= 30
9889.288  1640.19897.2661637.9259900.5131636.0779910.3841628.6289915.9651625.004
9931.417 1617.969936.6481615.4369946.4291609.692 9950.181607.6779961.272 1602.08
9963.712 1601.089977.2441593.7769990.7761586.109    99991583.541   100011583.201
10004.461582.88210005.561582.97810018.661590.32510019.651591.44510026.151597.517
10034.021603.79610050.721613.98910057.571616.78510069.541619.87810081.511625.257
10087.111626.87110093.481628.346 10105.31635.34710117.421639.735 10123.31641.438
#Mann= 3 , 0 , 0
9889.288    0.04       09889.288    0.04       0 10123.3    0.04       0
#XS Ineff= 2 , 0
       0                               0
Bank Sta=9889.288,10123.3
Exp/Cntr=0.3,0.1

Type RM Length L Ch R = 1 ,10245.88,37.235300,37.235300,37.235300
XS GIS Cut Line= 3
521357.180551678787003.433613554521479.153476506787009.306384012
521559.113505006787047.253516182
#Sta/Elev= 28
9918.906 1625.159926.7351625.0979936.7461614.6499946.7581605.4379951.4771603.851
 9956.771602.1069966.781 1598.789976.7931592.7539986.8041585.5739996.816 1581.32
10006.831582.56910016.84 1587.1910026.851591.88910036.861596.82410041.021598.559
10047.491599.397 10054.31600.74410058.561601.86210069.631605.94710077.621611.532
 10080.71613.59210091.771619.28210100.95 1623.8910102.841625.12210113.911627.652
10124.271631.57810124.971631.80410129.531633.197
#Mann= 3 , 0 , 0
9918.906    0.04       09918.906    0.04       010129.53    0.04       0
#XS Ineff= 2 , 0
       0                               0
Bank Sta=9918.906,10129.53
Exp/Cntr=0.3,0.1

Type RM Length L Ch R = 1 ,10208.65,151.256900,151.256900,151.256900
XS GIS Cut Line= 3
521354.101481974787037.806429431521524.893786877787045.767087728
521543.216259837787062.154889628
#Sta/Elev= 24
9905.7021608.9359906.6021608.7119916.6131605.0859926.6231604.0319936.6341602.251
9946.6451596.8699956.6561588.9959966.6671583.1839976.6781577.1469986.6891574.041
9996.6991572.98310006.711572.51910016.721573.84910026.731579.54610036.741584.918
10046.751591.98510056.761598.681 10060.21601.54910066.781607.07210076.681617.419
10076.821617.52410090.241622.52510090.53 1622.5410101.261622.467
#Mann= 3 , 0 , 0
9905.702    0.04       09905.702    0.04       010101.26    0.04       0
#XS Ineff= 2 , 0
       0                               0
Bank Sta=9905.702,10101.26
Exp/Cntr=0.3,0.1

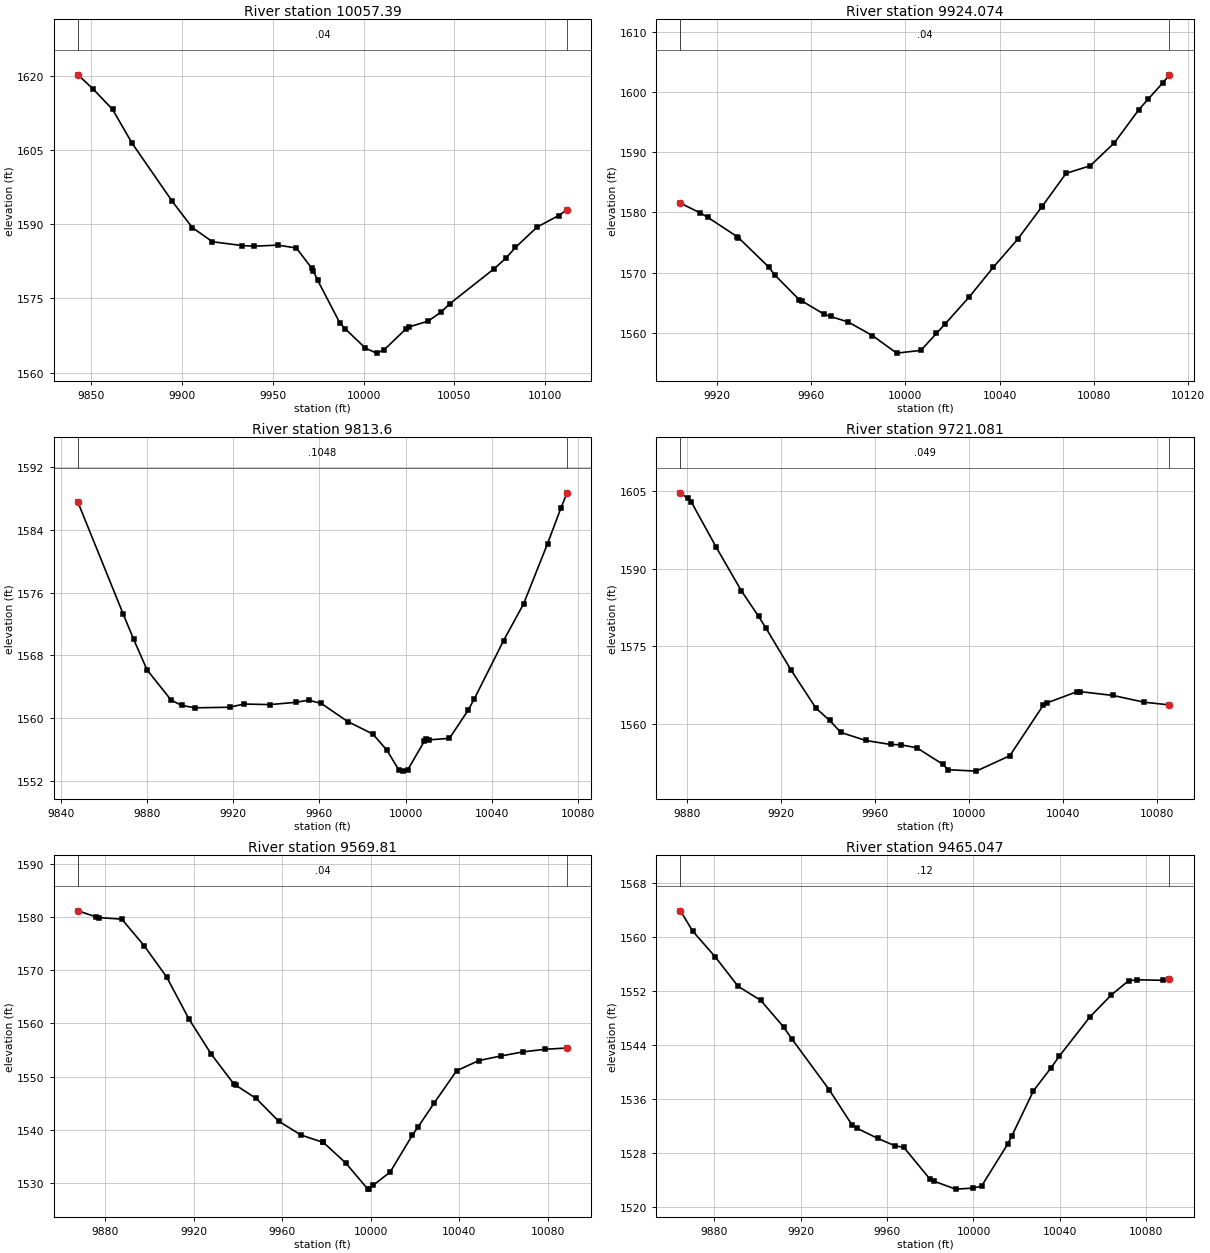
Type RM Length L Ch R = 1 ,10057.39,133.315400,133.315400,133.315400
XS GIS Cut Line= 6
521287.309293282787017.157762398521297.613375485787044.560691714
521318.469731778787088.013849109521344.446243227787132.228419393
521401.584992468787215.211485133521423.252782226787248.899971411
#Sta/Elev= 30
9842.5711620.1699850.9491617.2849861.6331613.1759872.3341606.3719894.5191594.594
9905.611 1589.289916.703 1586.439932.938 1585.669939.747 1585.539952.679 1585.75
9962.9431585.1629971.3271581.1269972.292 1580.539974.7111578.617 9986.921570.004
9989.7231568.882   100011564.92810007.161563.916 10011.31564.57510023.411568.843
10024.911569.20310035.511570.37410042.651572.19410047.621573.93410072.081581.008
 10078.41583.10310083.72 1585.2810095.611589.388 10107.51591.72210112.141592.878
#Mann= 3 , 0 , 0
9842.571    0.04       09842.571    0.04       010112.14    0.04       0
#XS Ineff= 2 , 0
       0                               0
Bank Sta=9842.571,10112.14
Exp/Cntr=0.3,0.1

Type RM Length L Ch R = 1 ,9924.074,110.474100,110.474100,110.474100
XS GIS Cut Line= 3
521280.284468859787115.965619802521247.718139529787155.768911198
521212.980721593787307.745114699
#Sta/Elev= 29
9904.7131581.5389913.0581579.9329916.386 1579.17 9928.851575.9389929.3071575.804
9942.2271570.8849944.6421569.6229955.1481565.4569956.1411565.284 9965.611563.075
 9968.341562.7039975.8681561.7649986.1261559.5129996.3841556.59710006.64 1557.05
10013.22 1559.87 10016.91561.44110027.16 1565.9510037.421570.91110047.671575.542
10057.931580.945 10058.11581.03110068.191586.49610078.451587.76710088.711591.596
10098.961597.04810102.971598.83910109.221601.56310112.04 1602.89
#Mann= 3 , 0 , 0
9904.713    0.04       09904.713    0.04       010112.04    0.04       0
#XS Ineff= 2 , 0
       0                               0
Bank Sta=9904.713,10112.04
Exp/Cntr=0.3,0.1

Type RM Length L Ch R = 1 ,  9813.6,92.518600,92.518600,92.518600
XS GIS Cut Line= 6
521213.723249257787015.131455913521205.795947254787037.851286963
521184.193817586787080.906651318521134.372479171787156.655597746
521116.556793034787186.627989948521103.734499151787213.174798982
#Sta/Elev= 30
9847.8031587.4779868.8461573.2339873.641 1570.069879.8641566.1659891.0521562.309
 9895.94 1561.63 9902.241561.3219918.2391561.3939924.9391561.8039936.9131561.731
9948.8881562.0189954.9271562.2969960.8631561.8769973.1051559.5789984.8131557.981
9991.2831555.9479996.7881553.462    9999 1553.26   100011553.41810008.731557.062
10009.551557.308 10010.71557.23610020.411557.43410029.041560.99310032.041562.503
10045.571569.88410054.871574.56310065.971582.20810072.141586.71210075.051588.695
#Mann= 3 , 0 , 0
9847.803  0.1048       09847.803  0.1048       010075.05  0.1048       0
#XS Ineff= 2 , 0
       0                               0
Bank Sta=9847.803,10075.05
Exp/Cntr=0.3,0.1

Type RM Length L Ch R = 1 ,9721.081,151.270900,151.270900,151.270900
XS GIS Cut Line= 3
521116.005429834786980.634429082521082.715404302787075.438632205
521007.450998753787152.150430158
#Sta/Elev= 26
9877.3141604.7039880.3491603.6329881.9411602.9329892.5391594.1569903.1381585.787
9910.5321580.7899913.7371578.4589924.3351570.3889934.9341563.0069940.7151560.642
9945.5321558.3049956.1311556.744 9966.731555.9729970.8971555.9169977.7931555.344
 9988.811552.1529991.1881551.08610003.091550.81310017.371553.79510031.651563.611
10033.221564.03210045.921566.19310047.231566.20910061.231565.46610074.481564.159
10085.261563.636
#Mann= 3 , 0 , 0
9877.314   0.049       09877.314   0.049       010085.26   0.049       0
#XS Ineff= 2 , 0
       0                               0
Bank Sta=9877.314,10085.26
Exp/Cntr=0.3,0.1

Type RM Length L Ch R = 1 , 9569.81,104.763500,104.763500,104.763500
XS GIS Cut Line= 5
520976.256965101786875.471481204520958.751886398786984.857190773
 520956.82660681787005.372544155520956.703384548787007.368744627
520949.373271898787094.723206039
#Sta/Elev= 29
9867.6171581.1929875.5711580.0829877.267  1579.99887.3941579.6389897.521 1574.62
9907.648 1568.779917.7761560.8349927.9031554.188 9938.031548.6459938.8551548.405
9948.1571545.8989958.2851541.6299968.4121539.0169978.3951537.6349978.5381537.619
9988.5821533.7769998.6261528.837    9999 1528.95   100011529.56810008.661532.022
10018.69 1538.9510021.371540.56910028.731545.10910038.761551.111 10048.81553.024
10058.83 1553.8910068.871554.662 10078.91555.15110088.661555.385
#Mann= 3 , 0 , 0
9867.617    0.04       09867.617    0.04       010088.66    0.04       0
#XS Ineff= 2 , 0
       0                               0
Bank Sta=9867.617,10088.66
Exp/Cntr=0.3,0.1

Type RM Length L Ch R = 1 ,9465.047,139.026000,139.026000,139.026000
XS GIS Cut Line= 3
520798.713791639786879.675958976520823.887877673  786955.1982169
520905.550156534787077.384634212
#Sta/Elev= 29
9864.247 1563.859869.8591560.876  9880.41557.0179890.9411552.6769901.4821550.583
9912.0221546.6579915.7481544.9279933.1041537.3879943.6451532.1929945.8561531.683
9955.6441530.1499963.8521529.0279967.6711528.8519979.6991524.1799981.8491523.795
9991.7271522.6389999.8451522.78510003.751523.08510015.781529.26410017.841530.557
10027.811537.20810035.841540.55310039.84 1542.3610053.831548.09510063.891551.399
10071.831553.48310075.921553.63910087.951553.55710090.821553.742
#Mann= 3 , 0 , 0
9864.247    0.12       09864.247    0.12       010090.82    0.12       0
#XS Ineff= 2 , 0
       0                               0
Bank Sta=9864.247,10090.82
Exp/Cntr=0.3,0.1

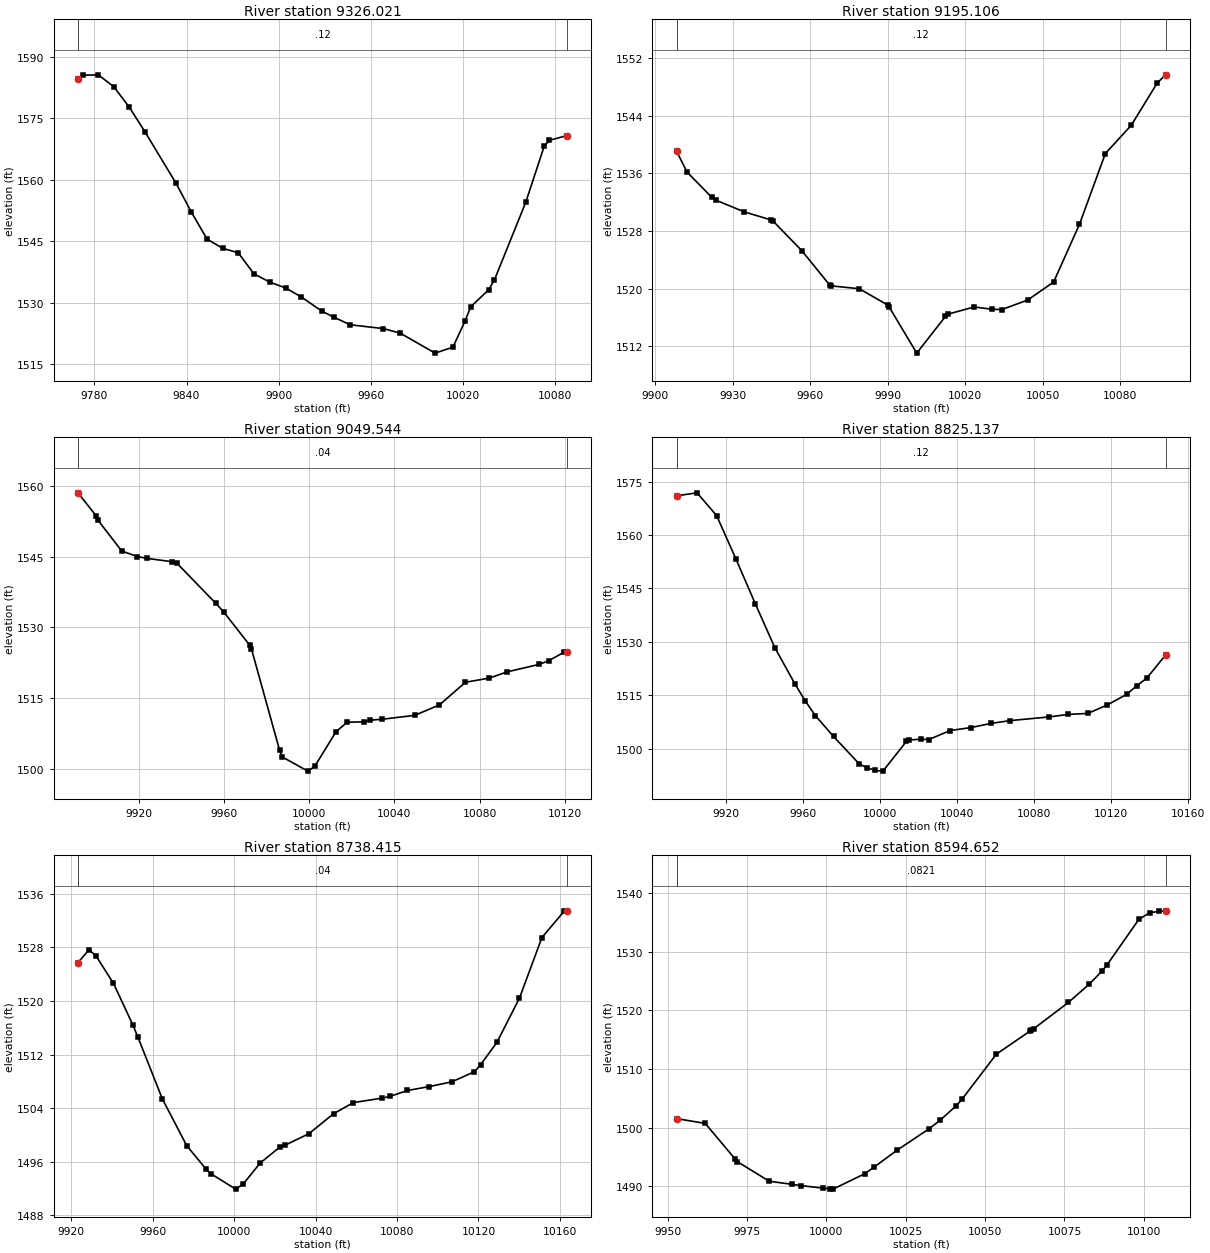
Type RM Length L Ch R = 1 ,9326.021,130.914500,130.914500,130.914500
XS GIS Cut Line= 6
520726.293314457786891.898595005 520743.48950842787002.521168202
520754.973829985787047.653573066520770.806967556787088.095291018
520783.691971302787112.580786541520831.306411211787187.200634004
#Sta/Elev= 30
9769.3591584.714 9772.491585.5349782.5831585.6419792.6751582.7359802.7681577.727
9812.8611571.779 9833.091559.2129843.2411552.0449853.3921545.4929863.544 1543.25
9873.6951542.1459883.8881537.0099894.2061534.9929904.5251533.5569914.8441531.336
9927.9011527.944 9935.791526.4349946.5291524.5619968.0071523.6379979.1341522.516
10001.831517.63310013.441519.09310021.171525.36610025.061528.96310036.681533.123
10040.441535.53410060.791554.44510072.851568.20710076.261569.63910087.551570.784
#Mann= 3 , 0 , 0
9769.359    0.12       09769.359    0.12       010087.55    0.12       0
#XS Ineff= 2 , 0
       0                               0
Bank Sta=9769.359,10087.55
Exp/Cntr=0.3,0.1

Type RM Length L Ch R = 1 ,9195.106,145.562200,145.562200,145.562200
XS GIS Cut Line= 3
520710.911491781786991.424340636520657.493309349787101.330715999
520661.791324019787168.256944567
#Sta/Elev= 26
9908.319 1539.049912.2951536.1819921.8421532.6989923.4131532.2839934.5321530.645
9944.7191529.5439945.6511529.3619956.7691525.2489967.5951520.4639967.8881520.379
9979.0061519.9749990.1251517.6859990.4711517.49910001.241511.02910012.361516.126
10013.351516.44610023.48 1517.4410030.521517.119 10034.21517.08110044.221518.407
10054.241520.90610064.261528.92910074.281538.759 10084.31542.67610094.321548.533
10097.581549.688
#Mann= 3 , 0 , 0
9908.319    0.12       09908.319    0.12       010097.58    0.12       0
#XS Ineff= 2 , 0
       0                               0
Bank Sta=9908.319,10097.58
Exp/Cntr=0.3,0.1

Type RM Length L Ch R = 1 ,9049.544,224.406900,224.406900,224.406900
XS GIS Cut Line= 4
520479.878996164786967.745239243520516.922625184787025.117689073
520562.064293504787077.074664742 520609.38133651787156.281293944
#Sta/Elev= 30
9891.5261558.5279900.1621553.5849900.9671552.6929912.0651546.1869919.4021545.014
9923.9681544.6239935.8711543.9059937.8381543.6519956.274 1535.069959.8181533.318
9972.1341526.2119972.9091525.4779986.1571503.9019987.3811502.5229999.4041499.513
10002.631500.52610012.651507.89110017.881509.887 10025.91509.96210028.651510.308
10034.371510.52310049.531511.33810061.171513.56210073.371518.36310084.47 1519.23
10092.871520.55610107.771522.12510112.371522.90410119.421524.68410120.911524.856
#Mann= 3 , 0 , 0
9891.526    0.04       09891.526    0.04       010120.91    0.04       0
#XS Ineff= 2 , 0
       0                               0
Bank Sta=9891.526,10120.91
Exp/Cntr=0.3,0.1

Type RM Length L Ch R = 1 ,8825.137,86.721900,86.721900,86.721900
XS GIS Cut Line= 6
520364.666566795787226.114007043520400.131339645787229.490465851
520430.251399285787222.734833853520481.144327229 787191.52367668
520529.551927155787176.040084006 520604.17167329787185.457561084
#Sta/Elev= 30
9894.5781571.0129905.1131571.8419915.2611565.4539925.2621553.3069935.3161540.718
 9945.461528.3759955.8641518.2039961.3281513.3419966.5151509.2559975.9531503.391
9989.4071495.6079993.557  1494.69997.5511493.84210001.58 1493.6610013.74    1502
10015.111502.41410021.221502.61810025.451502.54410036.441505.06410047.421505.913
 10057.61507.06710067.771507.86110087.861508.88810097.861509.59710107.861509.867
10117.981512.23510128.131515.26110133.281517.63610138.471519.77210148.231526.262
#Mann= 3 , 0 , 0
9894.578    0.12       09894.578    0.12       010148.23    0.12       0
#XS Ineff= 2 , 0
       0                               0
Bank Sta=9894.578,10148.23
Exp/Cntr=0.3,0.1

Type RM Length L Ch R = 1 ,8738.415,143.763100,143.763100,143.763100
XS GIS Cut Line= 3
520420.492447674787329.892405063520555.214669883 787240.30907172
520626.048003197787206.975738391
#Sta/Elev= 30
9923.3331525.7289928.7461527.6579932.1691526.7549940.7551522.6349950.2291516.469
9952.7641514.6059964.7731505.3689976.7821498.3679986.3491494.8539988.7911494.157
 10000.81491.89310004.411492.63210012.81 1495.7910022.471498.17610024.821498.421
10036.83 1500.1910048.84 1503.1610058.591504.82110072.851505.49510076.651505.756
10085.121506.62910095.941507.21510106.991507.93110118.041509.42710121.071510.484
10129.091513.81810140.141520.421 10151.21529.48210162.251533.47210163.411533.439
#Mann= 3 , 0 , 0
9923.333    0.04       09923.333    0.04       010163.41    0.04       0
#XS Ineff= 2 , 0
       0                               0
Bank Sta=9923.333,10163.41
Exp/Cntr=0.3,0.1

Type RM Length L Ch R = 1 ,8594.652,243.789500,243.789500,243.789500
XS GIS Cut Line= 6
520599.753388643787373.824466065520603.641220719787337.668976352
520601.225358456787312.101241916520605.933299035 787286.58528316
520615.492176265787264.114661962520640.992622095787231.702850623
#Sta/Elev= 29
9952.8451501.5159961.8141500.7099971.3441494.5659971.9681494.1699981.9731490.844
9989.3081490.2989991.9961490.099    9999 1489.66   100011489.55310002.081489.494
 10012.11492.12710015.011493.23810022.231496.122 10032.41499.80110035.811501.237
10040.951503.74610042.681504.79510053.541512.50910064.121516.44210064.411516.552
10065.371516.87410076.241521.33410082.821524.46310086.711526.61810088.371527.707
10098.431535.49810101.881536.64810104.72 1536.8610106.851536.964
#Mann= 3 , 0 , 0
9952.845  0.0821       09952.845  0.0821       010106.85  0.0821       0
#XS Ineff= 2 , 0
       0                               0
Bank Sta=9952.845,10106.85
Exp/Cntr=0.3,0.1

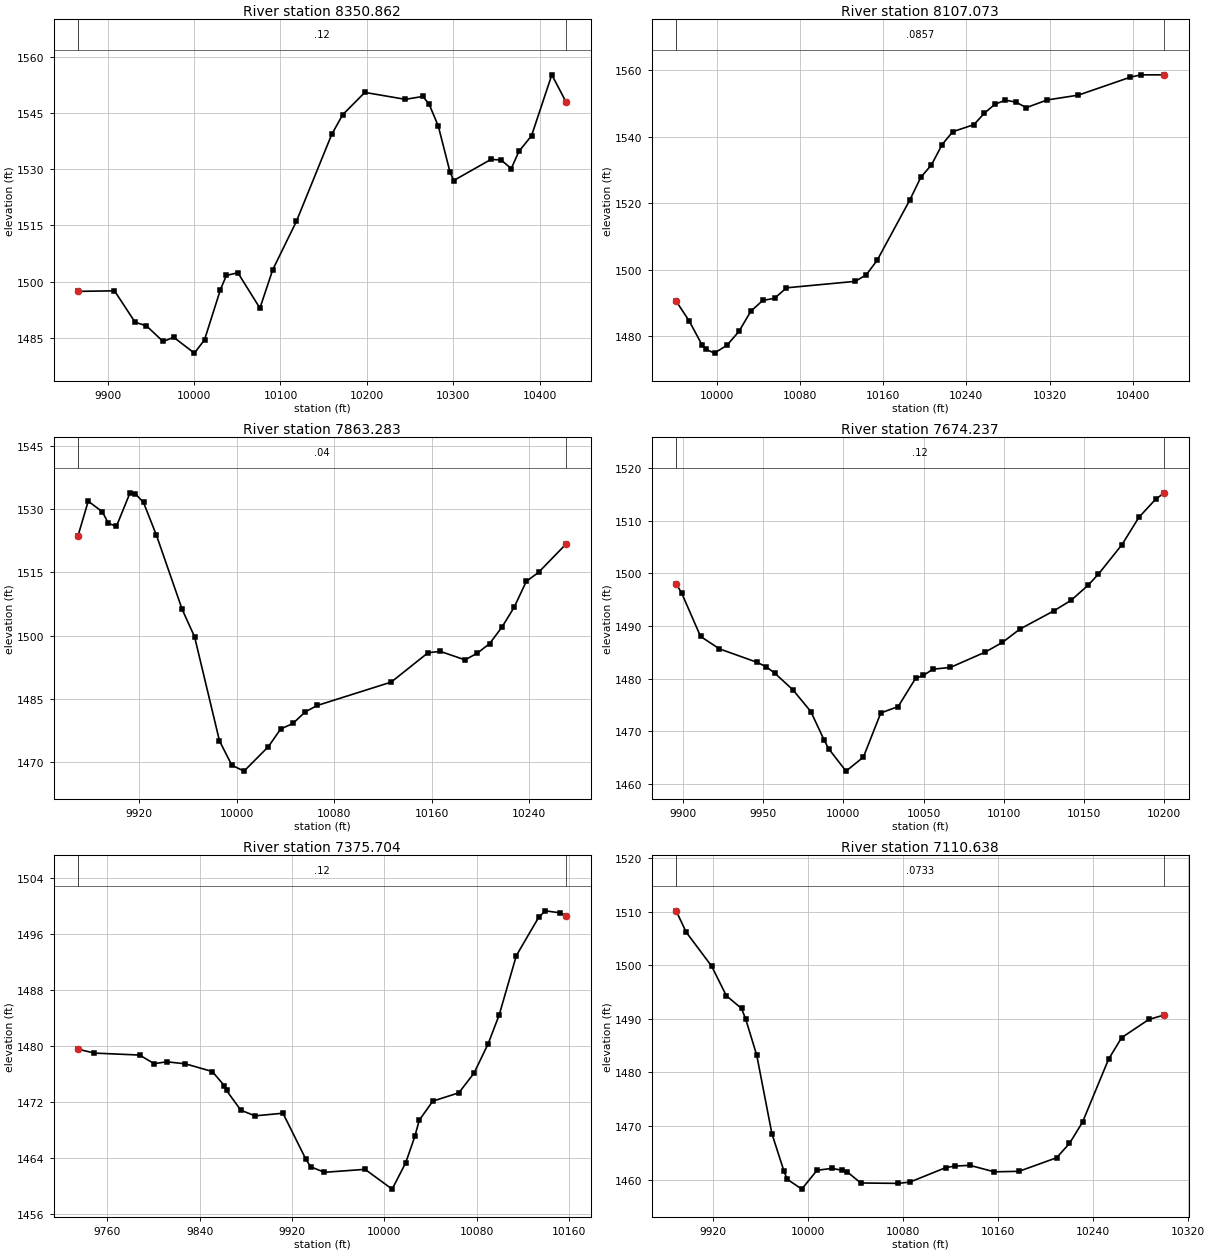
Type RM Length L Ch R = 1 ,8350.862,243.789500,243.789500,243.789500
XS GIS Cut Line= 6
 520589.46131587787435.368761599520647.138319075787502.080587819
520707.793242276787543.229571804520801.283597618787634.638825282
520853.648087323787702.333628118520953.622667909787859.214738712
#Sta/Elev= 30
9865.7711497.3739908.0151497.5229931.8631489.1269944.9931488.1739964.1571483.992
9976.5171485.111 10000.41480.88110012.121484.42810030.551497.84910037.411501.631
10050.671502.35310076.211492.89210091.071503.18210118.361516.05310159.241539.296
10171.881544.54210197.551550.51410244.37 1548.6610264.62 1549.4310271.741547.442
10282.461541.54310295.891529.37410300.291526.97710343.421532.61810355.141532.458
10366.871530.16910375.641534.73210390.321538.94210413.781555.20710430.44 1547.86
#Mann= 3 , 0 , 0
9865.771    0.12       09865.771    0.12       010430.44    0.12       0
#XS Ineff= 2 , 0
       0                10041.88       0
Bank Sta=9865.771,10430.44
Exp/Cntr=0.3,0.1

Type RM Length L Ch R = 1 ,8107.073,243.789500,243.789500,243.789500
XS GIS Cut Line= 6
 520501.16567874787424.638326257520441.782407075 787522.18830125
 520399.31567359787631.811959237520381.727691561787736.721892148
520381.265184551787812.075192764520386.876108348787867.445376769
#Sta/Elev= 30
9960.8311490.4959973.4311484.4869985.5911477.3929989.2441475.9919997.7511474.813
10009.771477.19310021.24 1481.3410032.671487.416 10044.11490.68610055.521491.327
10066.951494.48610133.011496.43810143.591498.35710154.121502.74910185.711521.008
10196.151527.775 10206.41531.52710216.651537.63510226.891541.51510247.26 1543.65
10257.341547.11510267.421549.78710277.491551.01710287.571550.43410297.651548.773
10317.671551.08310347.681552.53510397.811557.96310407.861558.63910430.421558.653
#Mann= 3 , 0 , 0
9960.831  0.0857       09960.831  0.0857       010430.42  0.0857       0
#XS Ineff= 2 , 0
       0                               0
Bank Sta=9960.831,10430.42
Exp/Cntr=0.3,0.1

Type RM Length L Ch R = 1 ,7863.283,189.046000,189.046000,189.046000
XS GIS Cut Line= 6
520221.982593387787237.994285434 520248.45627901787286.258058384
520257.182527751787311.290192381520266.050159007787359.866301715
 520263.91040203787431.487192899520241.071857645787627.628931271
#Sta/Elev= 30
9869.9451523.5739878.3611531.8219889.9381529.313 9894.961526.5649901.5141525.879
9912.6411533.8019916.9511533.5769923.6891531.5199934.3371523.7239955.3741506.206
9965.576  1499.79985.9821475.0569996.1051469.28210006.141467.88510026.151473.705
10036.181477.868 10046.21479.16610056.231481.90910066.261483.44510126.77 1488.97
10157.041495.93410167.131496.23810187.321494.23610197.411495.825 10207.51498.087
10217.531501.95510227.561506.66210237.591512.83410247.611514.95710270.311521.721
#Mann= 3 , 0 , 0
9869.945    0.04       09869.945    0.04       010270.31    0.04       0
#XS Ineff= 2 , 0
       0                               0
Bank Sta=9869.945,10270.31
Exp/Cntr=0.3,0.1

Type RM Length L Ch R = 1 ,7674.237,298.533000,298.533000,298.533000
XS GIS Cut Line= 6
520045.681408199 787342.03646768520073.132467807787386.322100335
520093.644871149  787428.7002946520140.991030644787541.356547541
520160.593002615787597.029493993 520167.85322331787620.214386029
#Sta/Elev= 30
9895.5841498.021 9899.071496.2419910.8361488.0049922.601 1485.659946.1321483.081
9951.9211482.2179957.3571480.9729968.4991477.8449979.6421473.7319987.7951468.412
 9990.731466.67410001.61  1462.410012.451465.058 10023.3 1473.4610034.151474.671
   100451480.02910049.891480.59510055.841481.78110066.691482.11210088.391485.014
10099.23 1486.8710110.081489.39310131.441492.89210142.04 1494.8710152.64 1497.73
10159.161499.86710173.851505.46810184.351510.63610194.831514.09910200.291515.311
#Mann= 3 , 0 , 0
9895.584    0.12       09895.584    0.12       010200.29    0.12       0
#XS Ineff= 2 , 0
       0                               0
Bank Sta=9895.584,10200.29
Exp/Cntr=0.3,0.1

Type RM Length L Ch R = 1 ,7375.704,265.066500,265.066500,265.066500
XS GIS Cut Line= 6
519695.979756087787384.307192534519761.081763685 787464.10104695
519797.371514201787514.607928082519885.877000511787655.615308404
519921.471826136 787706.26108332519940.309255538787728.922472636
#Sta/Elev= 30
9734.5661479.534 9748.681478.9679787.9561478.6889800.6461477.4499811.4581477.723
  9827.7 1477.439850.9981476.329 9861.431474.2939863.3121473.6159875.6261470.805
9887.9391469.9849912.1971470.3649931.919 1463.829936.1131462.7059948.0711461.908
9983.3261462.33110006.811459.50110018.551463.26910026.481467.053 10030.31469.366
10042.051472.098 10064.61473.28110077.74  1476.110089.961480.29110099.521484.412
10114.411492.91310133.691498.37510139.531499.32510152.541499.02910157.641498.518
#Mann= 3 , 0 , 0
9734.566    0.12       09734.566    0.12       010157.64    0.12       0
#XS Ineff= 2 , 0
       0                               0
Bank Sta=9734.566,10157.64
Exp/Cntr=0.3,0.1

Type RM Length L Ch R = 1 ,7110.638,222.512600,222.512600,222.512600
XS GIS Cut Line= 6
519540.733249489787670.016756042519658.548639379787760.041763021
519670.516099459 787766.06806951519782.836082152787785.656143307
519828.028979633787800.778721808519906.262621803787839.944104432
#Sta/Elev= 30
9888.6961510.164 9897.221506.1669918.6061499.8429931.0211494.3139943.8021491.944
9947.3091489.9399956.5831483.2279969.364 1468.579979.4251461.6479982.1451460.099
9994.5121458.23110007.391461.75510019.961462.09410028.69 1461.7510032.541461.489
10044.231459.378 10075.51459.30210085.581459.54310115.811462.25310123.611462.537
10136.151462.669 10156.61461.45710177.441461.55410209.071464.08410219.93 1466.75
10230.921470.72510252.891482.48210263.88  1486.5 10286.81489.89410299.871490.736
#Mann= 3 , 0 , 0
9888.696  0.0733       09888.696  0.0733       010299.87  0.0733       0
#XS Ineff= 2 , 0
       0                               0
Bank Sta=9888.696,10299.87
Exp/Cntr=0.3,0.1