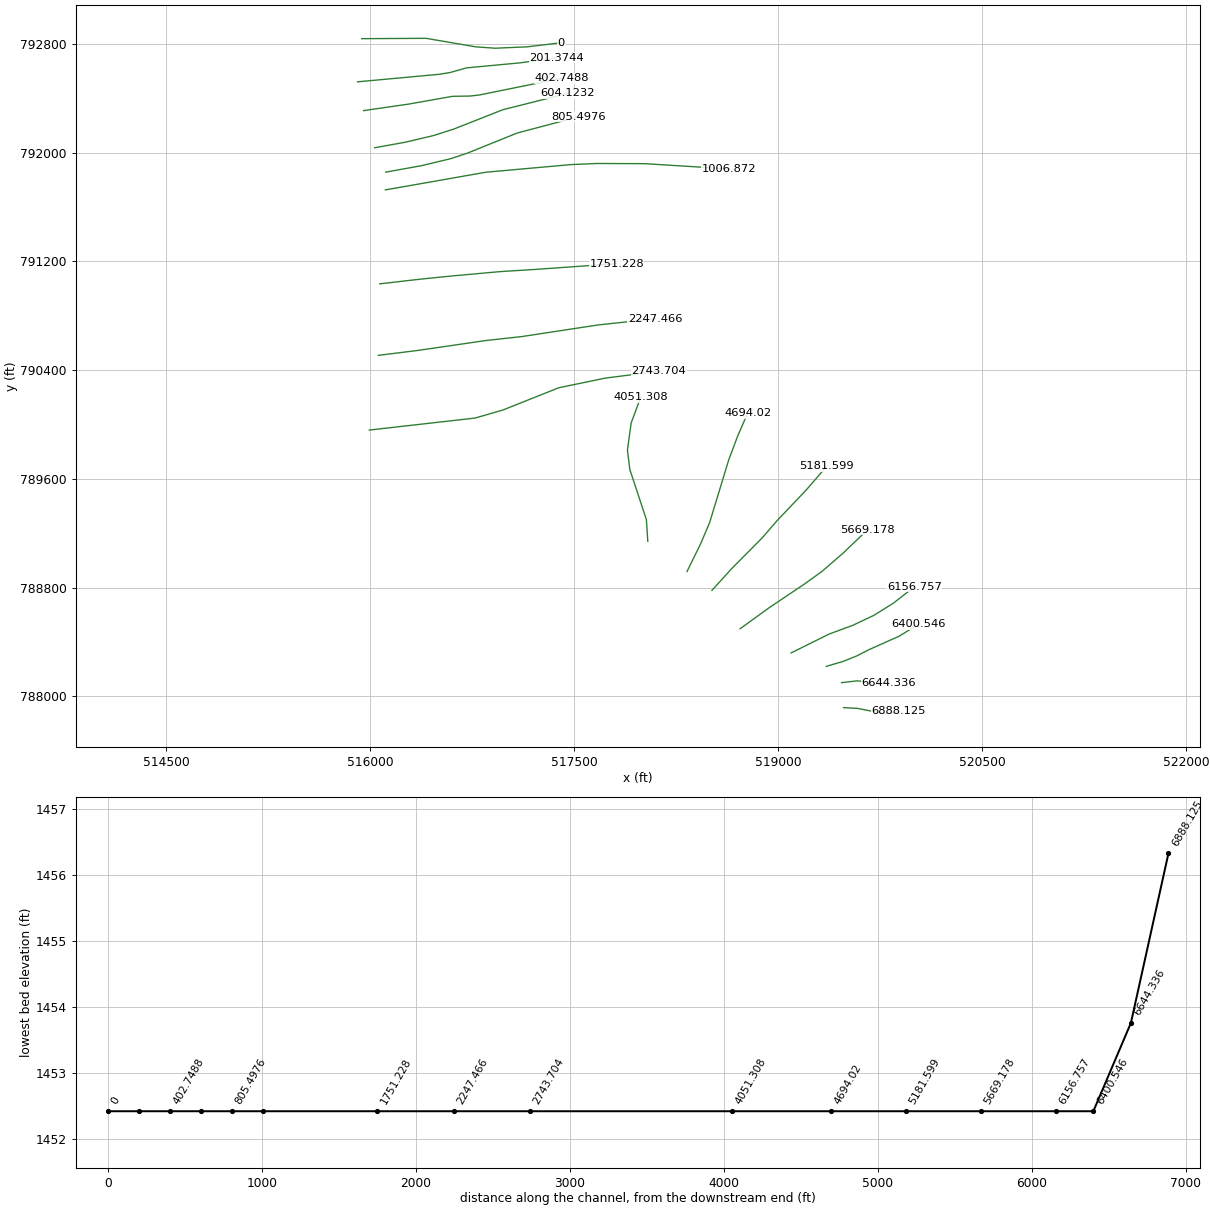
HEC-RAS study 5321_ras.prj: 5321

--- 5321_ras.g01 (geometry) --- (continued)

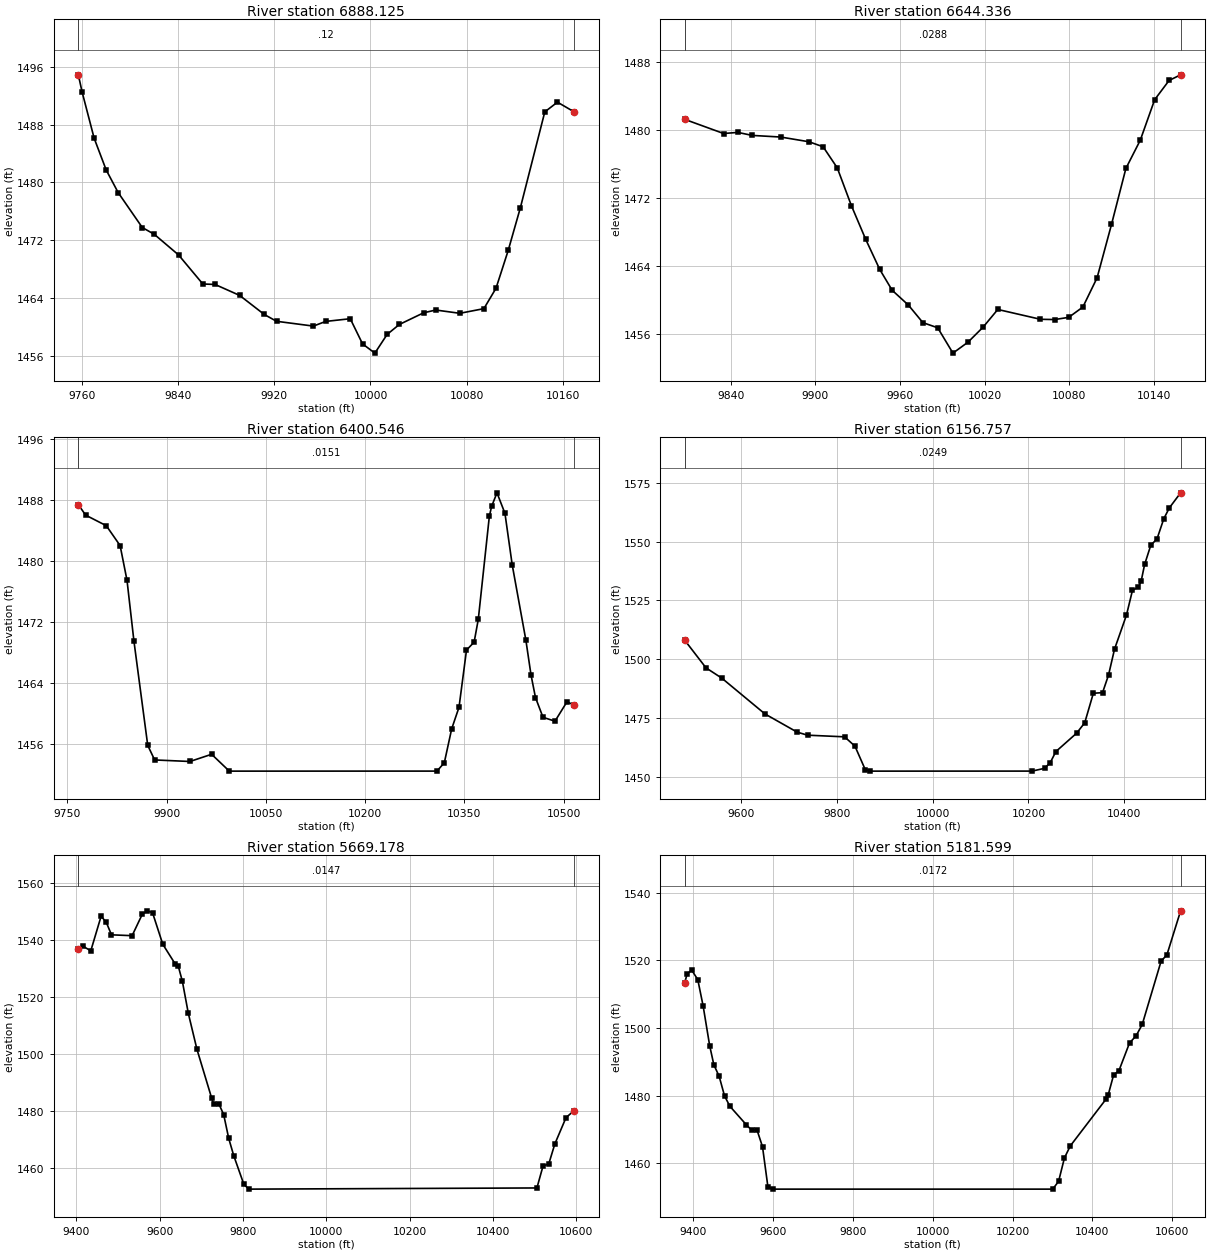
Type RM Length L Ch R = 1 ,6888.125,243.789500,243.789500,243.789500
XS GIS Cut Line= 6
519481.888809681787918.129548654519583.321636051787912.593817249
519771.984981596787876.066066116 519819.44369635787875.799810201
519864.180343032787883.007206529519888.237006201787890.659249417
#Sta/Elev= 30
9757.2781494.8879760.3961492.5219770.3991486.1139780.4011481.7139790.4021478.566
9810.4061473.7379820.4571472.7849840.5581469.9349860.6861465.9159870.8961465.845
9891.3151464.3299911.7351461.6929921.9451460.7459952.5751460.0799962.7851460.727
9983.204  1461.19993.4141457.61310003.641456.33410013.841458.92810023.941460.301
10044.141461.91910054.221462.30610074.221461.85110094.221462.49610104.29 1465.32
10114.421470.55810124.551476.48710144.831489.75410155.33  1491.110169.221489.755
#Mann= 3 , 0 , 0
9757.278    0.12       09757.278    0.12       010169.22    0.12       0
#XS Ineff= 2 , 0
       0                               0
Bank Sta=9757.278,10169.22
Exp/Cntr=0.3,0.1

Type RM Length L Ch R = 1 ,6644.336,243.789500,243.789500,243.789500
XS GIS Cut Line= 6
519467.833349794788101.893037498519579.805972844788114.741869166
519613.787174791788112.111484379519679.580602676788090.683902174
 519710.30019322788086.497723952519812.880265538788101.819980257
#Sta/Elev= 30
9807.5411481.2749835.0321479.6129845.1521479.7429855.2711479.3879875.5051479.196
9895.536 1478.649905.551 1478.059915.5671475.569 9925.591471.1179935.6191467.193
9945.649 1463.629954.4631461.1629965.9721459.4179976.2361457.3519986.7411456.746
9997.5341453.76310008.291455.06510018.95 1456.8310029.311458.90210059.551457.746
10069.571457.71310079.591457.976 10089.61459.18810099.681462.63310109.881468.909
10120.081475.50110130.281478.82710140.471483.59310150.671485.85310158.861486.518
#Mann= 3 , 0 , 0
9807.541  0.0288       09807.541  0.0288       010158.86  0.0288       0
#XS Ineff= 2 , 0
       0                               0
Bank Sta=9807.541,10158.86
Exp/Cntr=0.3,0.1

Type RM Length L Ch R = 1 ,6400.546,243.789500,243.789500,243.789500
XS GIS Cut Line= 6
519354.507372499788221.206303015519481.166502357788259.110277876
519580.707175136788299.291436344519660.222219229 788340.62705107
519889.826529711788443.190809011 520033.73855868 788531.00901787
#Sta/Elev= 30
9766.4251487.4339777.3771486.0539808.6911484.6619829.5681482.0519840.006 1477.48
9850.4441469.5149871.3211455.8069881.7591453.8949935.1131453.6919967.8751454.638
9994.6191452.42510308.481452.42910319.581453.52710330.671457.96810341.771460.811
10353.091468.32210364.611469.36910370.921472.36310387.64 1485.9110391.061487.199
10399.161488.978 10411.21486.286 10422.2 1479.5110442.871469.61210450.62 1465.05
10457.341462.09410468.721459.49510486.831458.98410504.931461.52610515.811461.108
#Mann= 3 , 0 , 0
9766.425  0.0151       09766.425  0.0151       010515.81  0.0151       0
#XS Ineff= 2 , 0
       0                10105.32       0
Bank Sta=9766.425,10515.81
Exp/Cntr=0.3,0.1

Type RM Length L Ch R = 1 ,6156.757,487.579000,487.579000,487.579000
XS GIS Cut Line= 6
 519095.46829945788320.244806883519376.467395008788459.744470715
 519549.25821256788523.339094415519704.315345029788596.659657461
519848.888180629788687.041259011520003.174915471788807.254850259
#Sta/Elev= 30
 9482.141508.0049526.3941496.3199559.4611491.9379649.5351476.7389716.6641469.006
9738.4871467.7029815.9291466.9979837.5721463.0329859.2151453.0069870.0371452.425
10207.62 1452.4410233.611453.61310245.321455.97110257.361460.75210300.591468.552
10317.541472.96710335.521485.50610354.81 1485.7910367.291493.27110379.771504.244
10404.731518.73410417.211529.19910429.731530.698 10435.41533.16710442.661540.235
10455.581548.45710468.511551.08810482.741559.69110494.371564.31410517.861570.686
#Mann= 3 , 0 , 0
 9482.14  0.0249       0 9482.14  0.0249       010517.86  0.0249       0
#XS Ineff= 2 , 0
       0                10138.54       0
Bank Sta=9482.14,10517.86
Exp/Cntr=0.3,0.1

Type RM Length L Ch R = 1 ,5669.178,487.579100,487.579100,487.579100
XS GIS Cut Line= 6
518720.987704373 788498.56909072518935.240236508788653.507819228
519191.920082861788825.692399541519323.813792807788920.820984191
519476.708947729789052.966852156519658.983468506 789227.41457604
#Sta/Elev= 30
9404.6951536.7749415.5081537.8529434.5641536.1479459.4421548.3639471.8811546.148
9484.3211541.7939533.8331541.4939558.3761549.0659570.6471550.2279582.9181549.548
9607.4611538.4849637.1791531.5829644.2741530.9919654.4321525.5159668.8171514.184
9689.4411501.5989724.8221484.4139729.4341482.5029742.5121482.247 9753.68 1478.64
9765.8031470.2499777.8921464.1749802.1711454.0919814.2751452.42510505.841452.836
10520.251460.41410534.561461.41810548.871468.29810575.721477.55510595.271480.039
#Mann= 3 , 0 , 0
9404.695  0.0147       09404.695  0.0147       010595.27  0.0147       0
#XS Ineff= 2 , 0
       0                               0
Bank Sta=9404.695,10595.27
Exp/Cntr=0.3,0.1

Type RM Length L Ch R = 1 ,5181.599,487.579000,487.579000,487.579000
XS GIS Cut Line= 6
518513.477705406788780.741481499518662.376966929788944.282044707
518882.399532895789165.889027499518992.075479966789292.796353946
519208.487039071 789520.55629583519357.093357058789692.501041739
#Sta/Elev= 30
9378.6751513.4659384.3861516.0149395.9661517.1629411.2091514.351 9424.621506.561
9440.9871494.8449451.4431489.1939464.8551485.7369478.2661479.9739491.6781476.912
9532.2711471.5259545.986 1469.879559.7011469.8839573.4161464.9699587.1311452.956
9600.8731452.42510300.781452.42510315.471454.71610330.171461.65610344.861465.202
10434.151478.98510439.991480.35510453.331486.14410466.661487.41710493.331495.641
10509.731497.72510525.131501.10410572.251519.73710587.111521.72710621.341534.677
#Mann= 3 , 0 , 0
9378.675  0.0172       09378.675  0.0172       010621.34  0.0172       0
#XS Ineff= 2 , 0
       0                               0
Bank Sta=9378.675,10621.34
Exp/Cntr=0.3,0.1

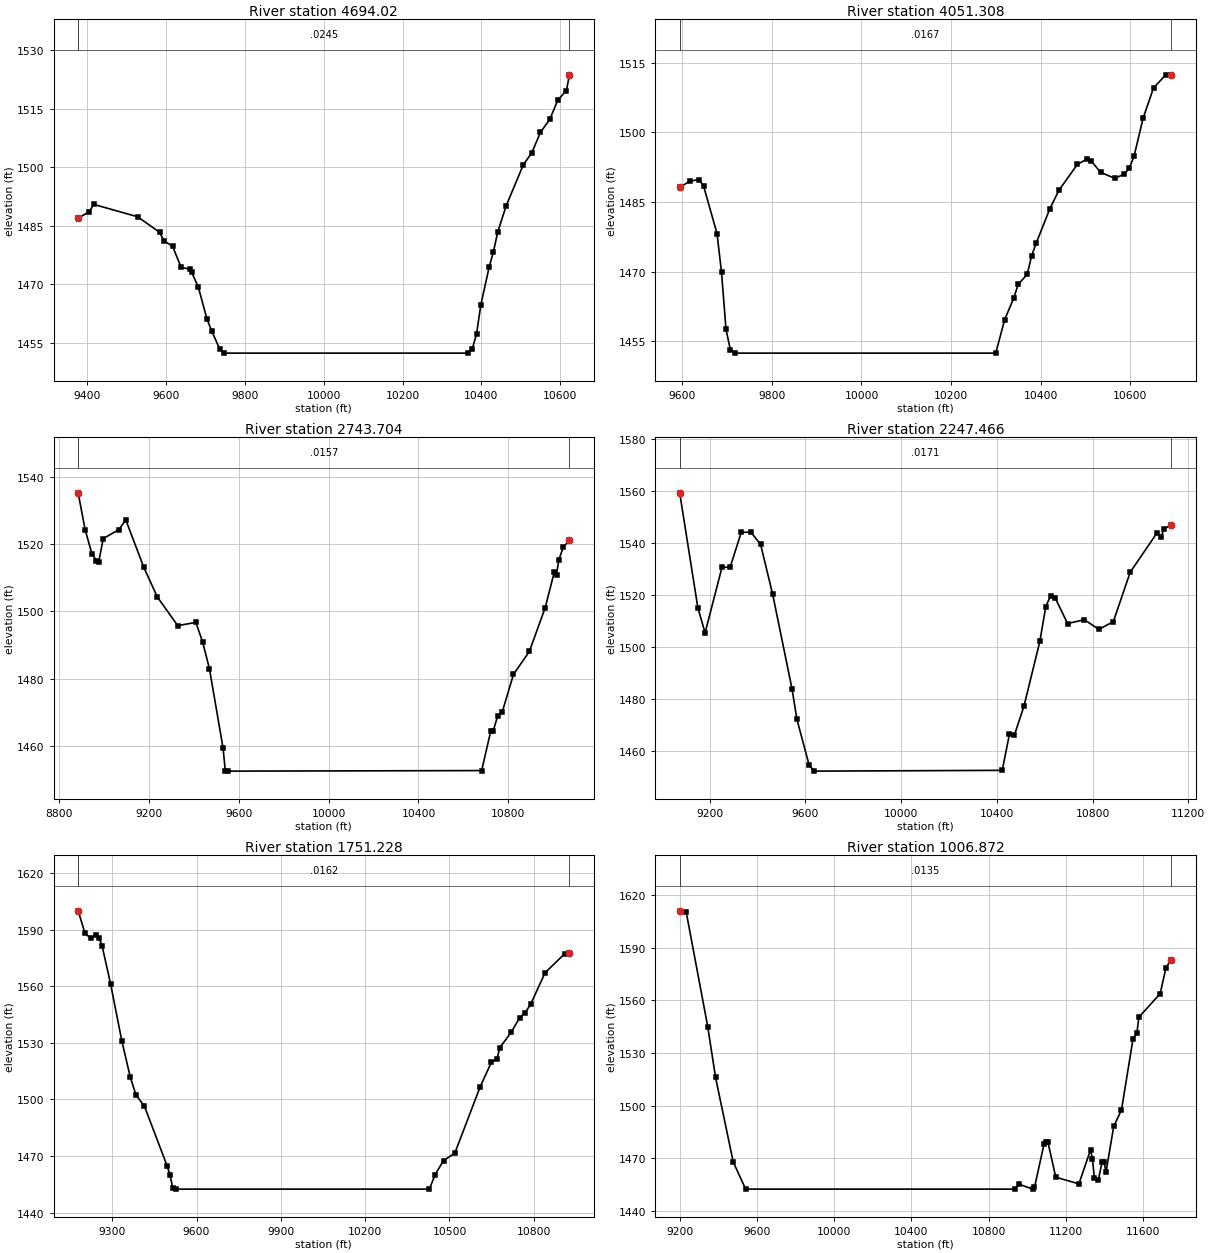
Type RM Length L Ch R = 1 , 4694.02,642.711700,642.711700,642.711700
XS GIS Cut Line= 6
518330.259442533788919.606093558518428.870807908789120.286884399
518496.910933495789280.241210848518637.027182837789740.735278863
518701.538284244789912.454520727518775.292758087 790082.21358017
#Sta/Elev= 30
9376.2231486.9499404.7481488.6669415.9811490.5139527.4951487.3329582.9031483.376
9593.9851481.2099615.9261479.8059637.7871474.3849659.6481473.9339664.561 1473.13
9681.5091469.3219703.3141461.1539715.2491458.1199735.6741453.5139746.4611452.425
 10366.31452.42510377.031453.57410387.761457.26510398.491464.69710419.951474.518
10430.681478.36410441.431483.40310463.121490.17710506.491500.64610528.171503.752
 10550.11508.94710574.251512.36110593.941517.20710615.87 1519.6610623.781523.684
#Mann= 3 , 0 , 0
9376.223  0.0245       09376.223  0.0245       010623.78  0.0245       0
#XS Ineff= 2 , 0
       0                               0
Bank Sta=9376.223,10623.78
Exp/Cntr=0.3,0.1

Type RM Length L Ch R = 1 ,4051.308,1307.604400,1307.604400,1307.604400
XS GIS Cut Line= 6
518041.628486865789141.745317064518031.438168954789301.074813375
517909.309491638 789670.53783276517891.732451158789812.817714205
517919.272651263790011.742131685517989.638606192790201.067294917
#Sta/Elev= 30
9594.1541488.123 9617.421489.4929637.4211489.7769647.4221488.435 9677.471478.169
9687.5041469.8489697.5371457.5389707.5711453.0449717.6381452.425 10299.71452.425
 10319.71459.65410339.761464.23510349.781467.21810369.911469.38910379.991473.431
10390.071476.11110420.511483.52110440.851487.49910481.991493.07310502.751494.186
10513.191493.76710534.051491.33510565.75 1490.0610586.971491.00210597.581492.195
10608.381494.78310628.561502.973 10651.91509.53210679.351512.34910691.131512.352
#Mann= 3 , 0 , 0
9594.154  0.0167       09594.154  0.0167       010691.13  0.0167       0
#XS Ineff= 2 , 0
       0                               0
Bank Sta=9594.154,10691.13
Exp/Cntr=0.3,0.1

Type RM Length L Ch R = 1 ,2743.704,496.237600,496.237600,496.237600
XS GIS Cut Line= 6
 515993.59168637789959.969823223516771.181071256 790048.03272377
516976.749013037790107.594233342517386.670632179790270.955149198
517730.657984432790342.246290448 518122.47995242790392.077026484
#Sta/Elev= 30
8885.9791535.284 8917.461524.2538947.5341517.0868967.5821515.1028977.6071514.679
8997.6551521.6589067.826 1524.359097.9311527.2579178.2371513.0849238.4811504.273
9328.9911495.7499409.5671496.6929439.8121490.9279470.0611482.9239530.7541459.309
 9540.871452.4269550.9861452.42510681.161452.586 10721.61464.38910731.711464.242
10751.921468.73410772.141469.93310822.65 1481.23 10893.21488.04510963.741501.092
11003.98 1511.6311014.031510.91711024.081515.27411044.181519.09211071.811521.211
#Mann= 3 , 0 , 0
8885.979  0.0157       08885.979  0.0157       011071.81  0.0157       0
#XS Ineff= 2 , 0
       0                               0
Bank Sta=8885.979,11071.81
Exp/Cntr=0.3,0.1

Type RM Length L Ch R = 1 ,2247.466,496.237600,496.237600,496.237600
XS GIS Cut Line= 6
 516059.59673523790509.230455388516354.863446928 790546.13459936
516849.400704013790618.246973396517116.850013994790647.727446844
517676.438183429790733.033313533 518095.09120333790778.159083154
#Sta/Elev= 30
9074.4751559.2589150.377 1515.159180.595 1505.49 9251.181530.6569285.4021530.725
9331.8491544.1139372.1841544.1439412.607 1539.449463.136 1520.269543.9821484.001
9564.1931472.3919614.7221454.9689634.9341452.42510422.441452.72210452.811466.713
10473.051466.17310513.541477.44810579.831502.30310604.491515.615 10624.71519.718
 10644.91518.71410695.411509.09310765.99 1510.5510826.451506.82110886.851509.821
10957.241528.77411067.781543.66711087.851542.46911097.891545.51211128.091546.751
#Mann= 3 , 0 , 0
9074.475  0.0171       09074.475  0.0171       011128.09  0.0171       0
#XS Ineff= 2 , 0
       0                               0
Bank Sta=9074.475,11128.09
Exp/Cntr=0.3,0.1

Type RM Length L Ch R = 1 ,1751.228,744.356400,744.356400,744.356400
XS GIS Cut Line= 6
516070.423822427791035.521784286516363.438345973791069.146105216
516591.054267025791092.328800037516953.347871769791125.210821708
517217.242589167791141.676726753 517812.09435939791183.951836166
#Sta/Elev= 30
9178.736 1599.919203.4741587.9579223.6051585.3239243.7361587.3099253.8021585.339
9263.8681581.4559294.0641561.3599334.3271530.9169364.5241511.7129384.6551502.322
9414.8521496.2989495.3471464.7799505.3991460.0619515.4511453.0699525.5021452.425
10428.691452.42810448.741460.06410478.821467.57610518.931471.45710609.171506.633
10649.281519.72110669.331521.59410679.361527.46510719.461535.49510749.54 1543.24
 10769.61545.97310789.651550.65310839.781567.02210909.911577.19710927.031577.348
#Mann= 3 , 0 , 0
9178.736  0.0162       09178.736  0.0162       010927.03  0.0162       0
#XS Ineff= 2 , 0
       0                               0
Bank Sta=9178.736,10927.03
Exp/Cntr=0.3,0.1

Type RM Length L Ch R = 1 ,1006.872,201.374400,201.374400,201.374400
XS GIS Cut Line= 6
516111.707674851791726.510874483516850.770073705 791856.46462832
517474.595902548791912.401287997517664.971464503791920.677118902
518020.560693315791919.268374531518641.198143809791880.758238703
#Sta/Elev= 30
9199.5491611.0539233.2861610.3489344.7571545.0659385.3561516.064 9476.851467.914
9541.1591452.425 10937.31452.425 10957.3 1455.2311027.311452.42511037.311453.377
11087.321478.40711097.321479.36211107.321479.01311147.341459.23311267.451455.416
11327.541474.78211337.561469.77811347.581458.55211367.611457.34711387.641468.122
11397.661467.89311407.671462.07911447.741488.208 11487.8 1497.5211547.951538.215
11568.011541.56511578.031550.45611688.381563.835 11718.51578.73311744.791583.087
#Mann= 3 , 0 , 0
9199.549  0.0135       09199.549  0.0135       011744.79  0.0135       0
#XS Ineff= 2 , 0
       0                10556.96       0
Bank Sta=9199.549,11744.79
Exp/Cntr=0.3,0.1

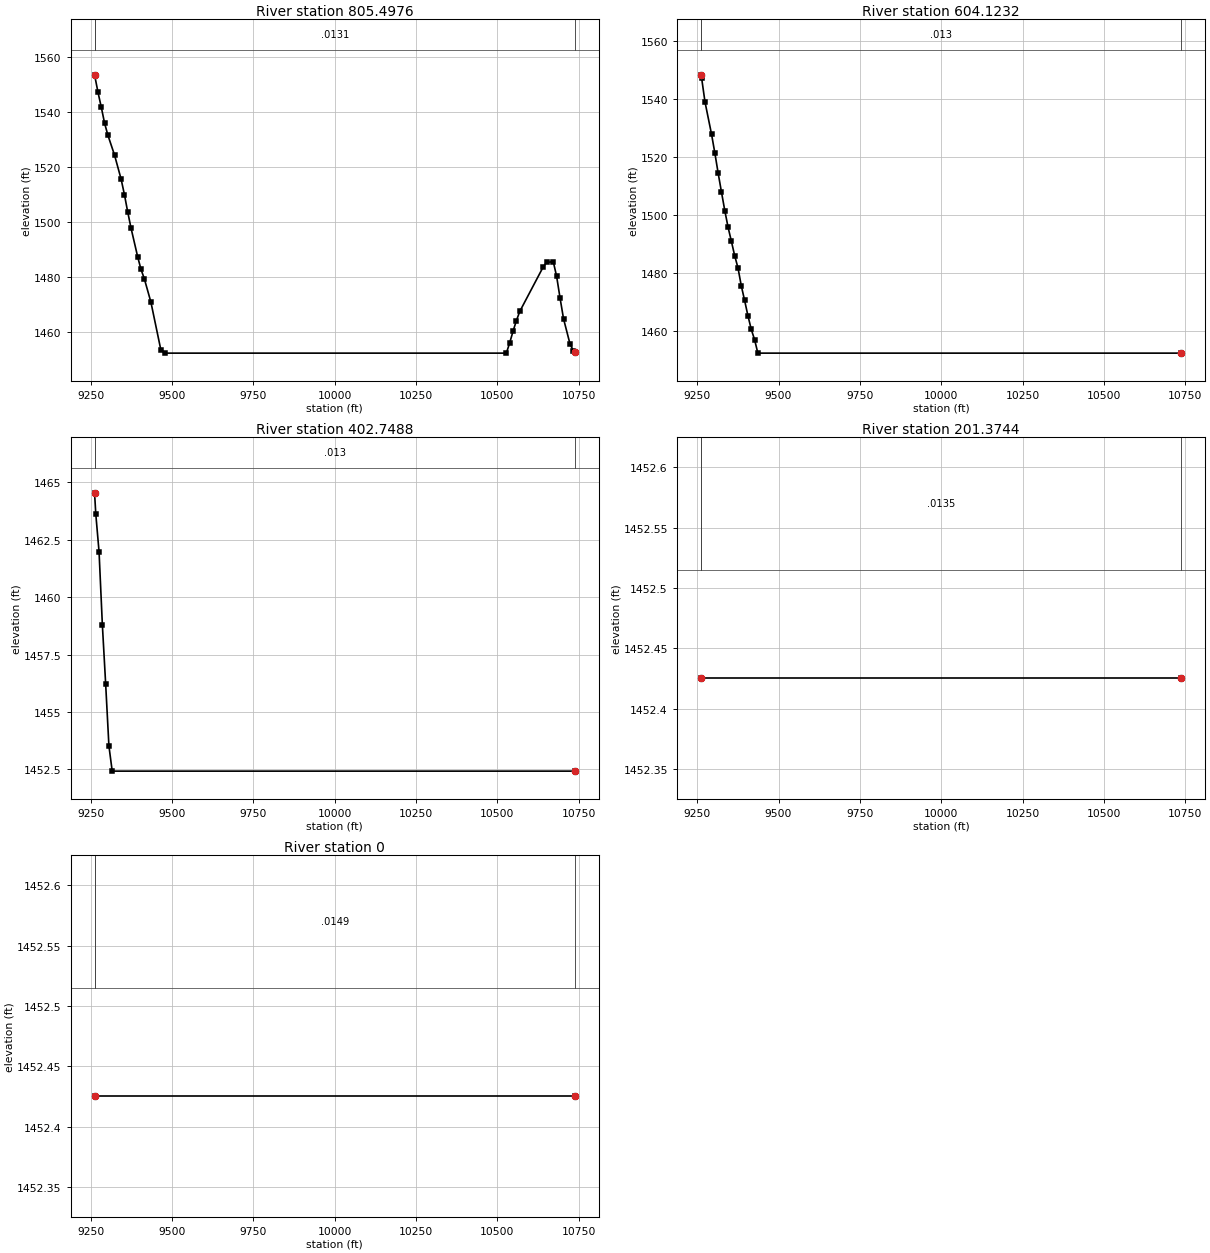
Type RM Length L Ch R = 1 ,805.4976,201.374400,201.374400,201.374400
XS GIS Cut Line= 6
516114.504084454791857.113030799516377.742674976791904.738357177
516593.698198758791956.513704606516718.889826254791998.373110364
517080.497288556792144.609915352517529.612915179792263.457419914
#Sta/Elev= 30
  9261.71553.6759272.3481547.2719282.4931541.8389292.6381536.0139302.7841531.681
9323.0741524.4849343.3641515.7039353.509  1510.19363.6541503.758  9373.81497.914
9394.1091487.5339404.2881482.9329414.466 1479.579434.824 1471.01 9465.361453.671
9477.0141452.42510527.451452.42510537.751456.14110548.061460.39810558.361464.237
10568.671467.582 10640.81483.78810651.111485.42510671.721485.70410682.021480.367
10692.331472.64710703.291464.91410723.251455.71610733.551453.314 10738.31452.834
#Mann= 3 , 0 , 0
  9261.7  0.0131       0  9261.7  0.0131       0 10738.3  0.0131       0
#XS Ineff= 2 , 0
       0                               0
Bank Sta=9261.7,10738.3
Exp/Cntr=0.3,0.1

Type RM Length L Ch R = 1 ,604.1232,201.374400,201.374400,201.374400
XS GIS Cut Line= 6
516032.992222611792036.525331929516259.238004434792077.405800266
516468.819287561792127.009585994516614.876193381792174.008471113
 516975.95641676792316.340615775517450.486330592792435.769562381
#Sta/Elev= 19
9261.6981548.2289263.7361546.9659273.8831538.8879294.1771527.6949304.3241521.213
9314.4711514.3079324.6181507.8289334.7661501.4729344.9131495.732 9355.061490.895
9365.2071485.9449375.3541481.7429385.5011475.5699395.6661470.5829405.8471465.311
9416.0291460.6319426.2111457.1029436.3931452.42510738.311452.425
#Mann= 3 , 0 , 0
9261.698   0.013       09261.698   0.013       010738.31   0.013       0
#XS Ineff= 2 , 0
       0                               0
Bank Sta=9261.698,10738.31
Exp/Cntr=0.3,0.1

Type RM Length L Ch R = 1 ,402.7488,201.374400,201.374400,201.374400
XS GIS Cut Line= 6
 515951.27387127 792309.67638018516280.316954968792357.203426277
516604.669871757 792414.66240207516734.592517187792416.815480748
516801.803579648 792424.39735137517406.275758255792547.175191294
#Sta/Elev= 8
9261.7331464.5439265.4941463.624 9275.591461.9679285.6851458.8059295.7811456.239
9305.8771453.5219315.9721452.425 10738.31452.425
#Mann= 3 , 0 , 0
9261.733   0.013       09261.733   0.013       0 10738.3   0.013       0
#XS Ineff= 2 , 0
       0                               0
Bank Sta=9261.733,10738.3
Exp/Cntr=0.3,0.1

Type RM Length L Ch R = 1 ,201.3744,201.374400,201.374400,201.374400
XS GIS Cut Line= 6
515906.756839565792521.413504372 516509.05902917 792576.93158621
516587.990431986792590.006675145516709.148006174792624.124149096
517101.018173544792660.819640756 517370.34251377 792698.09361731
#Sta/Elev= 2
9261.6971452.42510738.271452.425
#Mann= 3 , 0 , 0
9261.697  0.0135       09261.697  0.0135       010738.27  0.0135       0
#XS Ineff= 2 , 0
       0                               0
Bank Sta=9261.697,10738.27
Exp/Cntr=0.3,0.1

Type RM Length L Ch R = 1 ,       0,0.000000,0.000000,0.000000
XS GIS Cut Line= 6
515937.696864703792838.893428697516411.317867452792841.288640943
516776.004353511792778.762200368516918.284353304792768.579950804
517153.116070059792778.744522189 517405.64039652792808.706060091
#Sta/Elev= 2
9261.7071452.42510738.261452.425
#Mann= 3 , 0 , 0
9261.707  0.0149       09261.707  0.0149       010738.26  0.0149       0
#XS Ineff= 2 , 0
       0                               0
Bank Sta=9261.707,10738.26
Exp/Cntr=0.3,0.1